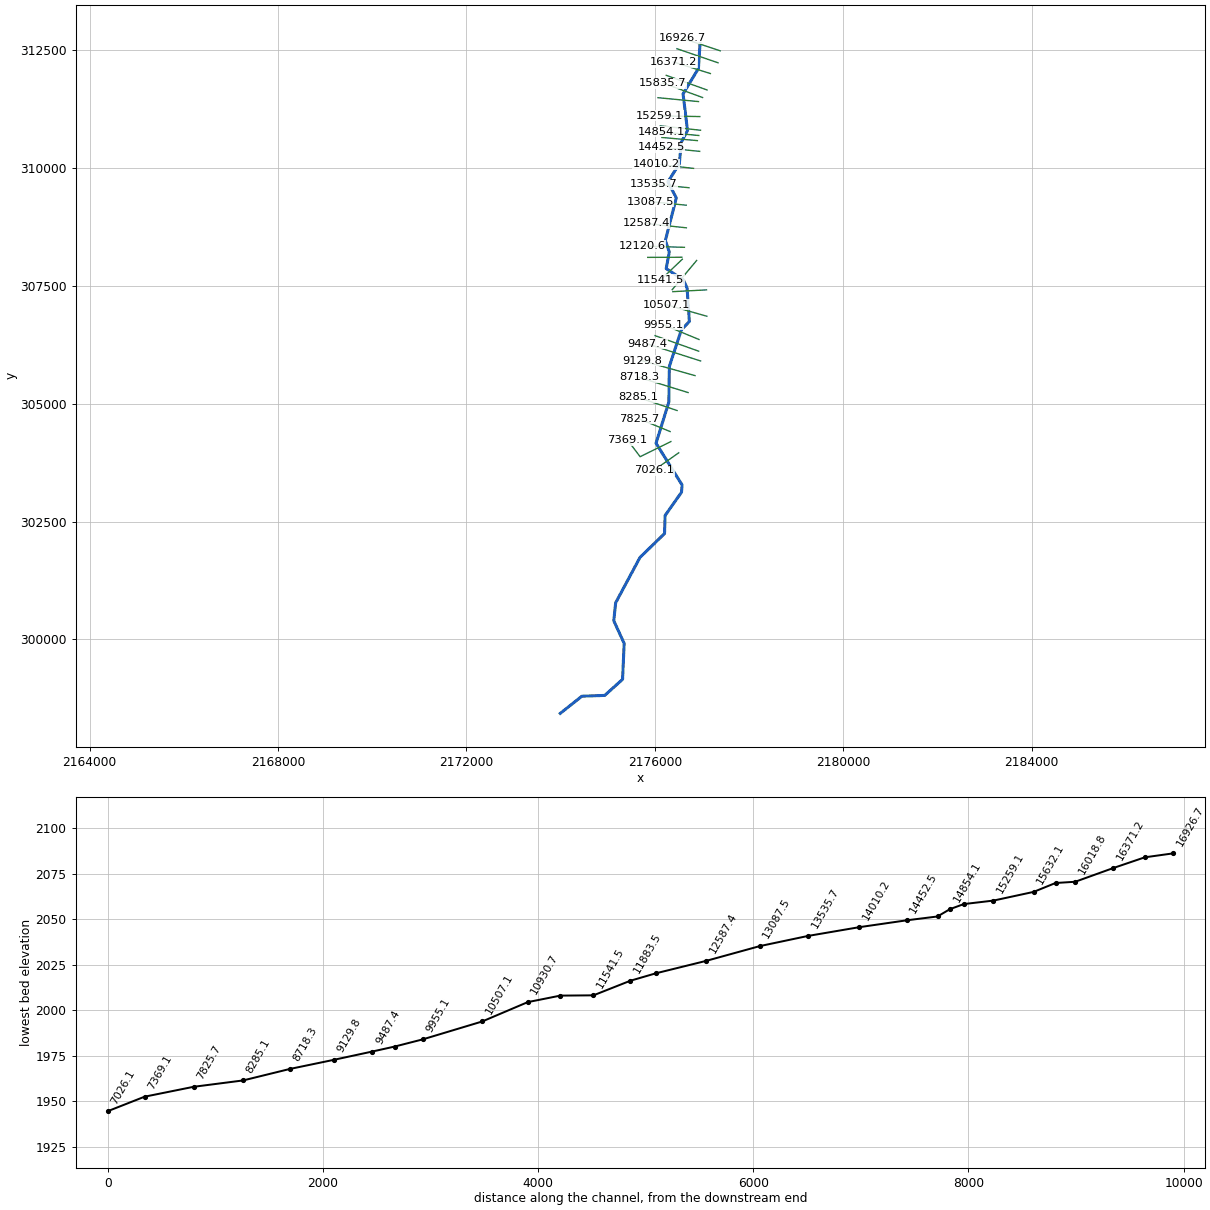
--- JerichDr.prj (project) ---

Proj Title=JerichDr
Current Plan=p01
Geom File=g01
Flow File=f01
Plan File=p01
DSS Export Rating Curves=0
DSS Export Rating Curve Sorted=0
DSS Export Volume Flow Curves=0
DXF OffsetX=0
DXF OffsetY=0
DXF ScaleX=0
DXF ScaleY=0

--- JerichDr.p01 (plan) ---

Plan Title=Floodplain
Program Version=4.00
Geom File=g01
Flow File=f01
K Sum by GR=0
Std Step Tol=0.01
Critical Tol=0.01
Num of Std Step Trials=20
Max Error Tol=0.3
Flow Tol Ratio=0.001
Split Flow NTrial=30
Split Flow Tol=0.02
Split Flow Ratio=0.02
Log Output Level=0
Friction Slope Method=1
Unsteady Friction Slope Method=2
Unsteady Bridges Friction Slope Method=1
Global Log Level=0
CheckData=False
Run HTab=0
Run UNet=0
Run PostProcess=0
UNET Theta=0
UNET Theta Warmup=0
UNET ZTol=0
UNET ZSATol=0
UNET MxIter=0
UNET MaxInSteps=0
UNET DtIC=0
UNET DtMin=0
UNET MaxCRTS=0
UNET WFStab=0
UNET SFStab=0
UNET WFX=0
UNET SFX=0
UNET DSS MLevel=0
UNET DZMax Abort=0
UNET Convert EG Bridges=0
UNET Use Existing IB Tables=0
UNET Froude Limit=0
UNET Froude Power=0
Write IC File=0
Echo Input=False
Echo Output=False
Write Detailed=0

--- JerichDr.f01 (steady flow) ---

Flow Title=NFF Regression Equation
Program Version=4.00
Number of Profiles=1
Profile Names=P100yr
River Rch & RM=JerichDr,Main      ,16926.7
578.2807
River Rch & RM=JerichDr,Main      ,16371.2
594.3168
River Rch & RM=JerichDr,Main      ,15259.1
659.3741
River Rch & RM=JerichDr,Main      ,13535.7
680.7000
River Rch & RM=JerichDr,Main      ,13087.5
798.0006
River Rch & RM=JerichDr,Main      ,10930.7
822.0363
River Rch & RM=JerichDr,Main      ,10507.1
912.9184
River Rch & RM=JerichDr,Main      ,7825.7
1008.596
River Rch & RM=JerichDr,Main      ,7369.1
1188.528
River Rch & RM=JerichDr,Main      ,6559.6
1193.566
River Rch & RM=JerichDr,Main      ,6263.1
1379.698
River Rch & RM=JerichDr,Main      ,3820.8
1405.532
River Rch & RM=JerichDr,Main      ,604.8
2072.273
River Rch & RM=JerichDr,Main      ,604.8
1558.163
Boundary for River Rch & Prof#=JerichDr,Main      ,1
Up Type=0
Dn Type=3
Dn Slope=0.006

--- JerichDr.g01 (geometry) ---

Geom Title=USGS 10m DEM
Program Version=4.00

River Reach=JerichDr        ,Main
Reach XY= 30
      2176960.44      312649.332     2176926.211      312116.772
     2176599.503      311577.457     2176694.815       310799.33
     2176563.565      310555.582     2176519.815      310091.519
     2176277.095      309710.698      2176455.97      309371.624
     2176224.503      308464.957     2176307.315      308222.769
      2176241.69      307869.644     2176605.753      307632.144
      2176685.44      307457.144     2176733.667      306747.013
     2176563.565      306569.644     2176308.878      305794.644
      2176297.94      305038.394     2176026.065      304164.957
      2176579.19      303279.019      2176566.69      303124.332
     2176218.253      302630.582     2176206.521      302247.578
      2175684.49      301740.242     2175168.253      300777.457
     2175128.727      300397.958     2175349.503      299916.519
     2175315.128      299154.019     2174937.003      298813.394
     2174451.065      298796.207     2173992.245      298432.107

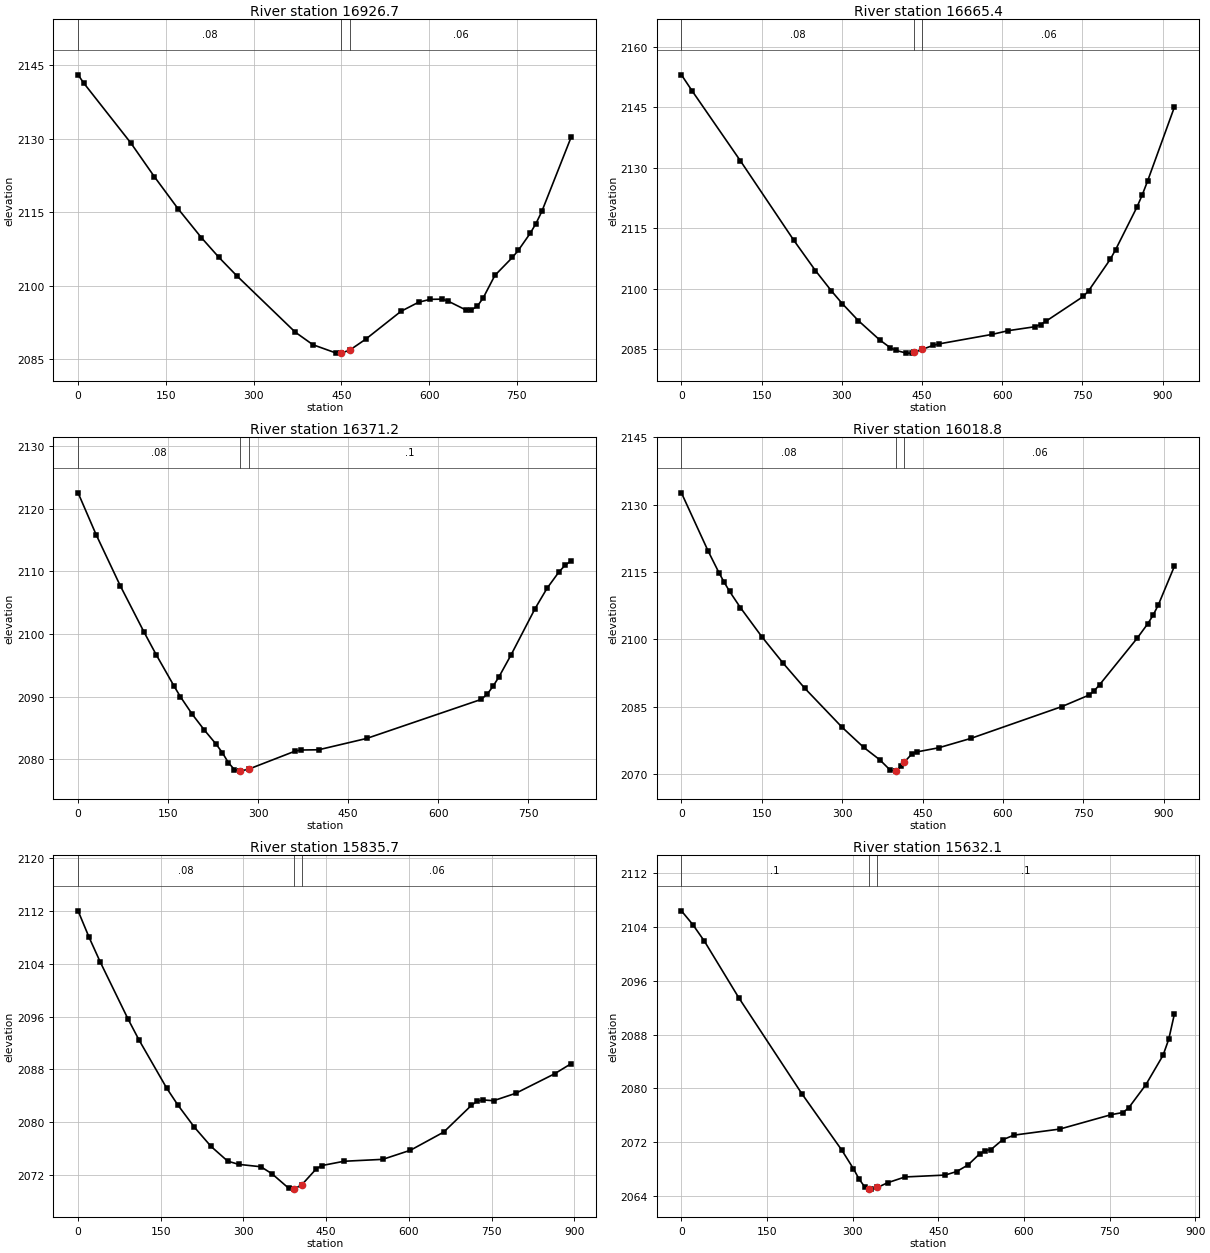
Type RM Length L Ch R = 1 ,16926.7 ,261.8,261.3,260.9
XS GIS Cut Line= 2
     2177389.838      312491.235     2176589.619      312756.116
#Sta/Elev= 30
       0 2143.07      10 2141.34    90.3 2129.12   130.4 2122.25   170.6 2115.74
   210.7  2109.8   240.8 2105.75   270.9 2102.04   371.3 2090.46   401.4  2087.9
   441.5 2086.18   450.3 2086.18   465.3 2086.87   491.7 2089.03   551.9 2094.72
     582 2096.58   602.1 2097.18   622.2 2097.21   632.2 2096.83   662.3 2095.04
   672.3 2095.02   682.4 2095.76   692.4 2097.44   712.5 2102.07   742.6 2105.76
   752.6  2107.2   772.7 2110.64   782.7 2112.66   792.8 2115.16   842.9 2130.34
#Mann= 3 , 0 , 0
       0     .08       0   450.3    .045       0   465.3     .06       0
Bank Sta=450.3,465.3
XS Rating Curve= 0 ,0
Exp/Cntr=0.3,0.1

Type RM Length L Ch R = 1 ,16665.4 ,297.2,294.3,295.4
XS GIS Cut Line= 2
     2177342.438      312237.507     2176469.725      312535.847
#Sta/Elev= 30
       0 2152.99      20 2149.02   110.3 2131.69   210.5 2111.94   250.6  2104.5
   280.7 2099.43   300.8 2096.31   330.8  2092.1   370.9  2087.3     391 2085.34
     401 2084.71     421 2084.03   431.1 2084.03   435.8 2084.23   450.8 2084.97
   471.2 2085.97   481.2  2086.3   581.4 2088.68   611.5  2089.6   661.6 2090.58
   671.7 2091.12   681.7 2091.92   751.9 2098.09   761.9 2099.53     802 2107.25
     812 2109.63   852.1 2120.22   862.2 2123.31   872.2 2126.76   922.3 2145.06
#Mann= 3 , 0 , 0
       0     .08       0   435.8    .045       0   450.8     .06       0
Bank Sta=435.8,450.8
XS Rating Curve= 0 ,0
Exp/Cntr=0.3,0.1

Type RM Length L Ch R = 1 ,16371.2 ,353.5,352.4,351.2
XS GIS Cut Line= 2
     2177180.002      312009.069     2176395.815      312254.128
#Sta/Elev= 30
       0 2122.55    30.1 2115.87    70.1 2107.75   110.2 2100.26   130.2  2096.7
   160.3 2091.63   170.3 2090.02   190.4 2087.17   210.4 2084.67   230.4 2082.37
   240.5 2081.04   250.5 2079.46   260.5 2078.35   269.9 2078.12   270.5 2078.11
   284.9 2078.45   360.7 2081.27   370.7 2081.48   400.8 2081.52   480.9 2083.33
   671.3 2089.55   681.3 2090.35   691.3 2091.64   701.4 2093.18   721.4 2096.66
   761.5 2104.07   781.5 2107.32   801.6 2109.96   811.6 2110.99   821.6  2111.7
#Mann= 3 , 0 , 0
       0     .08       0   269.9    .045       0   284.9      .1       0
Bank Sta=269.9,284.9
XS Rating Curve= 0 ,0
Exp/Cntr=0.3,0.1

Type RM Length L Ch R = 1 ,16018.8 ,182.9,183,183.1
XS GIS Cut Line= 2
     2177109.208      311660.542     2176243.335      311970.949
#Sta/Elev= 30
       0 2132.61      50  2119.6      70 2114.82      80 2112.64      90 2110.63
     110 2107.04     150 2100.55     190 2094.62     230 2089.08   299.9 2080.35
   339.9 2075.91   369.9 2073.14   389.9 2070.78   399.9  2070.6   400.6 2070.67
   409.9 2071.67   415.6 2072.59   429.9 2074.42   439.9  2074.9   479.9  2075.8
   539.9 2077.89   709.9 2084.99   759.9 2087.52   769.9 2088.48   779.9 2089.83
   849.8 2100.16   869.8 2103.42   879.8 2105.32   889.8 2107.68   919.8  2116.3
#Mann= 3 , 0 , 0
       0     .08       0   400.6    .045       0   415.6     .06       0
Bank Sta=400.6,415.6
XS Rating Curve= 0 ,0
Exp/Cntr=0.3,0.1

Type RM Length L Ch R = 1 ,15835.7 ,197.1,203.6,210.2
XS GIS Cut Line= 2
     2177013.984      311500.524     2176173.775      311806.768
#Sta/Elev= 30
       0 2111.97    20.1 2107.94    40.2 2104.24    90.4 2095.66   110.5 2092.46
   160.8 2085.17   180.9 2082.64     211 2079.27   241.2 2076.37   271.3 2074.15
   291.4 2073.66   331.6  2073.3   351.7 2072.24   381.8 2070.07   390.9 2069.93
   391.9 2069.92   405.9 2070.59   432.1 2072.99   442.1 2073.48   482.3 2074.13
   552.6 2074.42   602.9  2075.8   663.2 2078.54   713.4 2082.58   723.5 2083.19
   733.5  2083.4   753.6 2083.28   793.8  2084.4   864.1 2087.34   894.3 2088.88
#Mann= 3 , 0 , 0
       0     .08       0   390.9    .045       0   405.9     .06       0
Bank Sta=390.9,405.9
XS Rating Curve= 0 ,0
Exp/Cntr=0.3,0.1

Type RM Length L Ch R = 1 ,15632.1 ,369.4,373,376.3
XS GIS Cut Line= 2
     2176927.607      311414.147     2176067.768      311496.598
#Sta/Elev= 30
       0 2106.41    20.1 2104.35    40.2 2101.91   100.4  2093.5   210.9 2079.23
   281.2  2070.8   301.3 2068.07   311.4 2066.51   321.4 2065.33   328.3 2065.12
   331.4 2065.03   343.3 2065.28   361.6 2065.99   391.7 2066.84     462 2067.12
   482.1 2067.64   502.2 2068.63   522.3 2070.26   532.3 2070.77   542.4 2070.92
   562.5 2072.36   582.6 2073.06   662.9 2073.96   753.3 2076.11   773.4 2076.42
   783.4  2077.1   813.6 2080.55   843.7 2084.92   853.7 2087.31   863.8 2091.13
#Mann= 3 , 0 , 0
       0      .1       0   328.3    .045       0   343.3      .1       0
Bank Sta=328.3,343.3
XS Rating Curve= 0 ,0
Exp/Cntr=0.3,0.1

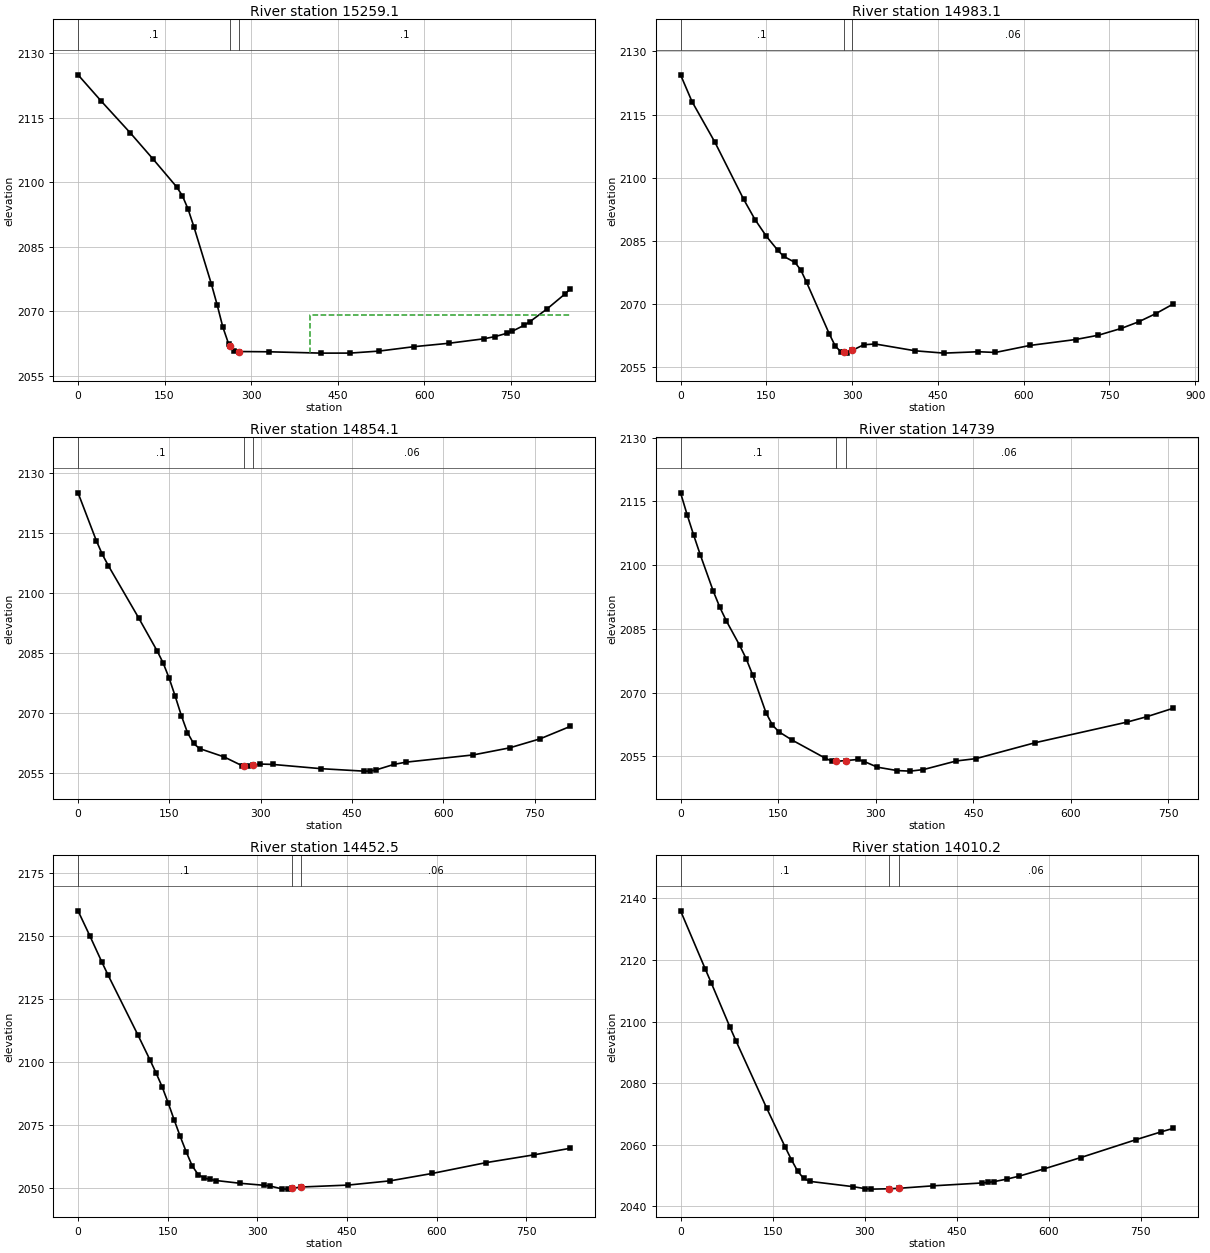
Type RM Length L Ch R = 1 ,15259.1 ,279.4,276,265.8
XS GIS Cut Line= 2
      2176955.09      311096.125      2176101.68      311111.066
#Sta/Elev= 30
       0 2124.94    40.2 2118.83    90.4 2111.47   130.5 2105.29   170.7 2098.93
   180.8 2096.87   190.8 2093.72   200.8 2089.64     231 2076.39     241 2071.56
     251 2066.32   261.1 2062.38   263.9 2061.94   271.1 2060.81   278.9 2060.63
   331.4 2060.57   421.8 2060.26     472 2060.27   522.2 2060.74   582.4 2061.76
   642.7 2062.55   702.9 2063.58     723 2064.11   743.1 2064.86   753.1 2065.37
   773.2 2066.73   783.2 2067.56   813.4 2070.57   843.5 2073.94   853.5  2075.2
#Mann= 3 , 0 , 0
       0      .1       0   263.9    .045       0   278.9      .1       0
#XS Ineff= 2 , 0
                          402.92         2069.04
Permanent Ineff=
       F       F
Bank Sta=263.9,278.9
XS Rating Curve= 0 ,0
Exp/Cntr=0.3,0.1

Type RM Length L Ch R = 1 ,14983.1 ,127.2,129,136.7
XS GIS Cut Line= 2
     2176970.795      310805.585     2176114.882      310899.814
#Sta/Elev= 30
       0 2124.43      20 2118.08    60.1 2108.42   110.1 2094.93   130.2 2090.06
   150.2 2086.06   170.2 2082.74   180.2 2081.34   200.2 2079.87   210.3 2078.07
   220.3 2075.19   260.3 2062.85   270.3  2060.1   280.4  2058.6     285  2058.5
   290.4 2058.38     300 2058.98   320.4 2060.33   340.4 2060.51   410.5 2058.89
   460.6 2058.34   520.7 2058.67   550.7  2058.5   610.8 2060.16   690.9 2061.57
   730.9  2062.6     771 2064.22     801 2065.77     831 2067.71   861.1 2069.97
#Mann= 3 , 0 , 0
       0      .1       0     285    .045       0     300     .06       0
Bank Sta=285,300
XS Rating Curve= 0 ,0
Exp/Cntr=0.3,0.1

Type RM Length L Ch R = 1 ,14854.1 ,115.6,115.1,115.7
XS GIS Cut Line= 2
     2176934.144       310694.22     2176129.264      310771.062
#Sta/Elev= 30
       0 2125.14      30 2113.19    39.9 2109.74    49.9 2106.89    99.8 2093.79
   129.8 2085.63   139.8 2082.58   149.7 2078.75   159.7 2074.21   169.7  2069.4
   179.7 2065.18   189.7 2062.46   199.6 2061.18   239.6 2059.11   269.5 2056.89
   272.2 2056.88   279.5 2056.85   287.2 2057.07   299.5 2057.31   319.4 2057.22
   399.3 2056.15   469.2 2055.54   479.1 2055.54   489.1 2055.83   519.1 2057.24
     539 2057.79   648.8 2059.59   708.7 2061.36   758.6 2063.61   808.5 2066.74
#Mann= 3 , 0 , 0
       0      .1       0   272.2    .045       0   287.2     .06       0
Bank Sta=272.2,287.2
XS Rating Curve= 0 ,0
Exp/Cntr=0.3,0.1

Type RM Length L Ch R = 1 ,14739   ,285.6,286.5,285.6
XS GIS Cut Line= 2
      2176904.05      310585.718     2176150.218      310652.463
#Sta/Elev= 30
       0 2116.99    10.1 2111.84    20.2 2107.01    30.3 2102.42    50.4 2093.81
    60.5 2090.02    70.6  2086.8    90.8 2081.12   100.9 2077.96     111 2074.09
   131.2 2065.32   141.3 2062.33   151.4 2060.76   171.5 2058.83     222 2054.61
   232.1  2053.9   238.6 2053.82   253.6 2054.01   272.4 2054.27   282.5 2053.78
   302.7 2052.45     333 2051.66   353.2 2051.53   373.4  2051.9   423.8 2053.92
   454.1 2054.47   544.9 2058.21   686.2 2063.06   716.4 2064.32   756.8  2066.3
#Mann= 3 , 0 , 0
       0      .1       0   238.6    .045       0   253.6     .06       0
Bank Sta=238.6,253.6
XS Rating Curve= 0 ,0
Exp/Cntr=0.3,0.1

Type RM Length L Ch R = 1 ,14452.5 ,442.7,442.3,438.4
XS GIS Cut Line= 2
      2176952.94      310357.624     2176133.203      310441.271
#Sta/Elev= 30
       0 2160.01    20.1 2149.89    40.2 2139.49    50.2 2134.51   100.5 2110.54
   120.6 2100.67   130.6 2095.58   140.7 2090.11   150.7  2083.8   160.8 2076.99
   170.8 2070.49   180.9 2064.34   190.9 2058.74     201  2055.2     211 2053.85
   221.1 2053.25   231.1 2052.84   271.3 2051.74   311.5 2050.94   321.6 2050.65
   341.7 2049.49   351.7 2049.42   357.4 2049.67   372.4 2050.25   452.2 2051.03
   522.5 2052.72   592.9 2055.66   683.3 2059.97   763.7 2063.07     824 2065.67
#Mann= 3 , 0 , 0
       0      .1       0   357.4    .045       0   372.4     .06       0
Bank Sta=357.4,372.4
XS Rating Curve= 0 ,0
Exp/Cntr=0.3,0.1

Type RM Length L Ch R = 1 ,14010.2 ,477.4,474.5,471.5
XS GIS Cut Line= 2
     2176822.065      309996.748     2176024.634      310085.971
#Sta/Elev= 27
       0 2135.91    40.1 2117.11    50.2 2112.45    80.2 2098.32    90.3 2093.72
   140.4 2071.88   170.5 2059.28   180.5 2055.23   190.6 2051.54   200.6 2049.08
   210.6 2048.15   280.8 2046.44   300.9 2045.77   310.9 2045.63   340.3 2045.75
   355.3 2045.89   411.2  2046.7   491.5 2047.63   501.5 2047.81   511.5 2048.09
   531.6 2048.88   551.6 2049.83   591.8 2052.16     652 2055.86   742.2 2061.67
   782.4 2064.16   802.4 2065.32
#Mann= 3 , 0 , 0
       0      .1       0   340.3    .045       0   355.3     .06       0
Bank Sta=340.3,355.3
XS Rating Curve= 0 ,0
Exp/Cntr=0.3,0.1

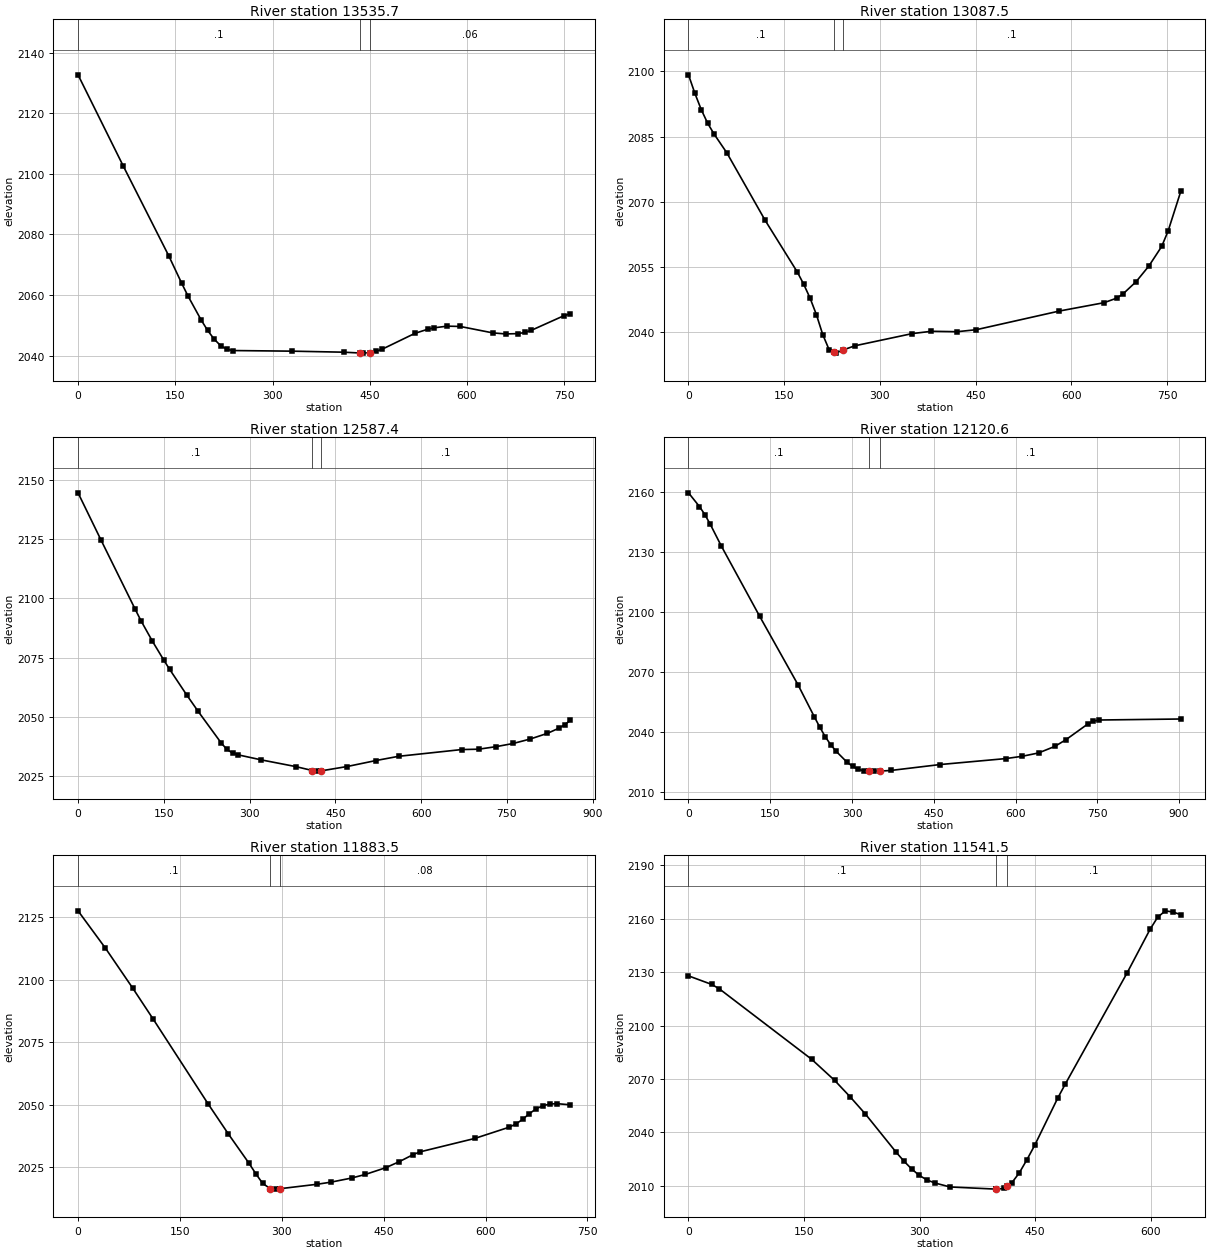
Type RM Length L Ch R = 1 ,13535.7 ,446.2,448.2,450.2
XS GIS Cut Line= 2
     2176726.241       309585.91     2175970.634      309661.192
#Sta/Elev= 30
       0 2132.67    69.9 2102.52   139.9 2072.97   159.9 2063.89   169.8 2059.61
   189.8 2051.82   199.8 2048.37   209.8  2045.5   219.8 2043.34   229.8 2042.05
   239.8 2041.69   329.7 2041.49   409.6 2041.15   434.8 2040.88   439.6 2040.84
   449.8 2040.97   459.6 2041.42   469.6 2042.18   519.6 2047.36   539.5 2048.73
   549.5  2049.2   569.5 2049.74   589.5 2049.64   639.4 2047.53   659.4 2047.17
   679.4 2047.28   689.4 2047.69   699.4 2048.38   749.4 2053.18   759.4 2053.82
#Mann= 3 , 0 , 0
       0      .1       0   434.8    .045       0   449.8     .06       0
Bank Sta=434.8,449.8
XS Rating Curve= 0 ,0
Exp/Cntr=0.3,0.1

Type RM Length L Ch R = 1 ,13087.5 ,500.6,500.1,499.5
XS GIS Cut Line= 2
     2176668.103      309215.404     2175900.253      309291.644
#Sta/Elev= 30
       0 2099.19      10 2094.94      20 2091.19    30.1 2088.05    40.1 2085.58
    60.1 2081.27   120.2 2065.74   170.4 2053.92   180.4 2051.13   190.4 2047.94
   200.4 2044.12   210.4 2039.52   220.5    2036   227.8 2035.45   230.5 2035.25
   242.8    2036   260.6 2036.93   350.7 2039.74   380.8 2040.27   420.9 2040.17
     451 2040.63   581.2 2044.92   651.4 2046.84   671.4  2047.9   681.4  2048.9
   701.5 2051.66   721.5 2055.25   741.6 2059.75   751.6 2063.26   771.6 2072.43
#Mann= 3 , 0 , 0
       0      .1       0   227.8    .045       0   242.8      .1       0
Bank Sta=227.8,242.8
XS Rating Curve= 0 ,0
Exp/Cntr=0.3,0.1

Type RM Length L Ch R = 1 ,12587.4 ,466.4,466.8,467.3
XS GIS Cut Line= 2
     2176670.477      308735.503     2175814.493      308827.514
#Sta/Elev= 30
       0 2144.46      40 2124.64   100.1 2095.29   110.1 2090.52   130.1 2081.88
   150.2 2073.83   160.2 2070.03   190.2 2059.17   210.2 2052.26   250.3 2039.01
   260.3 2036.27   270.3 2034.72   280.3 2033.96   320.3 2031.86   380.4 2029.04
     410 2027.36   420.4 2027.11     425 2027.22   470.5 2029.05   520.6 2031.56
   560.6 2033.36   670.7  2036.2   700.7 2036.36   730.8 2037.42   760.8 2038.76
   790.8 2040.65   820.9 2043.05   840.9 2045.21   850.9 2046.68   860.9 2048.49
#Mann= 3 , 0 , 0
       0      .1       0     410    .045       0     425      .1       0
Bank Sta=410,425
XS Rating Curve= 0 ,0
Exp/Cntr=0.3,0.1

Type RM Length L Ch R = 1 ,12120.6 ,234.9,237.1,239.3
XS GIS Cut Line= 2
     2176628.654      308321.548     2175725.989      308348.276
#Sta/Elev= 30
       0 2159.68    20.1 2152.81    30.1 2148.76    40.1 2143.84    60.2 2133.04
   130.4 2097.92   200.7 2063.64   230.8 2047.52   240.8 2042.34   250.8 2037.56
   260.9  2033.5   270.9 2030.21     291 2024.71     301 2022.66     311 2021.18
   321.1 2020.51   331.5 2020.35   341.2 2020.29   350.8 2020.29   371.3 2020.63
   461.6 2023.59     582 2026.57   612.1 2027.72   642.2  2029.4   672.3 2032.72
   692.4 2036.03   732.5  2043.9   742.5 2045.28   752.6 2045.89   903.1  2046.4
#Mann= 3 , 0 , 0
       0      .1       0   331.5    .045       0   350.8      .1       0
Bank Sta=331.5,350.8
XS Rating Curve= 0 ,0
Exp/Cntr=0.3,0.1

Type RM Length L Ch R = 1 ,11883.5 ,321.9,342.1,362.2
XS GIS Cut Line= 2
     2176575.677      308110.942      2175850.74      308108.154
#Sta/Elev= 30
       0 2127.64    40.3 2112.71    80.6 2096.66   110.8 2084.22   191.3 2050.43
   221.5 2038.23   251.7 2026.58   261.8 2022.35   271.8 2018.52   282.7 2016.45
     292  2016.2   297.7 2016.38   352.4 2018.16   372.5    2019   402.8 2020.64
   422.9 2022.07   453.1 2024.78   473.2 2027.22   493.4 2030.02   503.4 2031.11
     584 2036.48   634.3 2040.95   644.4 2042.23   654.5  2044.1   664.5  2046.4
   674.6 2048.37   684.7 2049.63   694.7 2050.25   704.8 2050.43   724.9 2049.97
#Mann= 3 , 0 , 0
       0      .1       0   282.7    .045       0   297.7     .08       0
Bank Sta=282.7,297.7
XS Rating Curve= 0 ,0
Exp/Cntr=0.3,0.1

Type RM Length L Ch R = 1 ,11541.5 ,304.1,307.2,310.3
XS GIS Cut Line= 2
     2176584.042      308069.118     2176121.198       307628.58
#Sta/Elev= 30
       0 2127.91      30 2123.13    39.9 2120.67   159.8  2081.1   189.7 2069.23
   209.7 2060.07   229.6 2050.36   269.6 2028.88   279.6 2023.94   289.5 2019.58
   299.5 2015.91   309.5 2013.38   319.5 2011.68   339.5 2009.41     399 2008.21
   399.4  2008.2   409.4 2008.57     414 2009.95   419.3 2011.55   429.3 2017.28
   439.3 2024.74   449.3 2032.75   479.2 2059.25   489.2 2067.29   569.1 2129.42
     599 2153.95     609 2160.86     619 2164.42     629 2163.73     639 2162.26
#Mann= 3 , 0 , 0
       0      .1       0     399    .045       0     414      .1       0
Bank Sta=399,414
XS Rating Curve= 0 ,0
Exp/Cntr=0.3,0.1

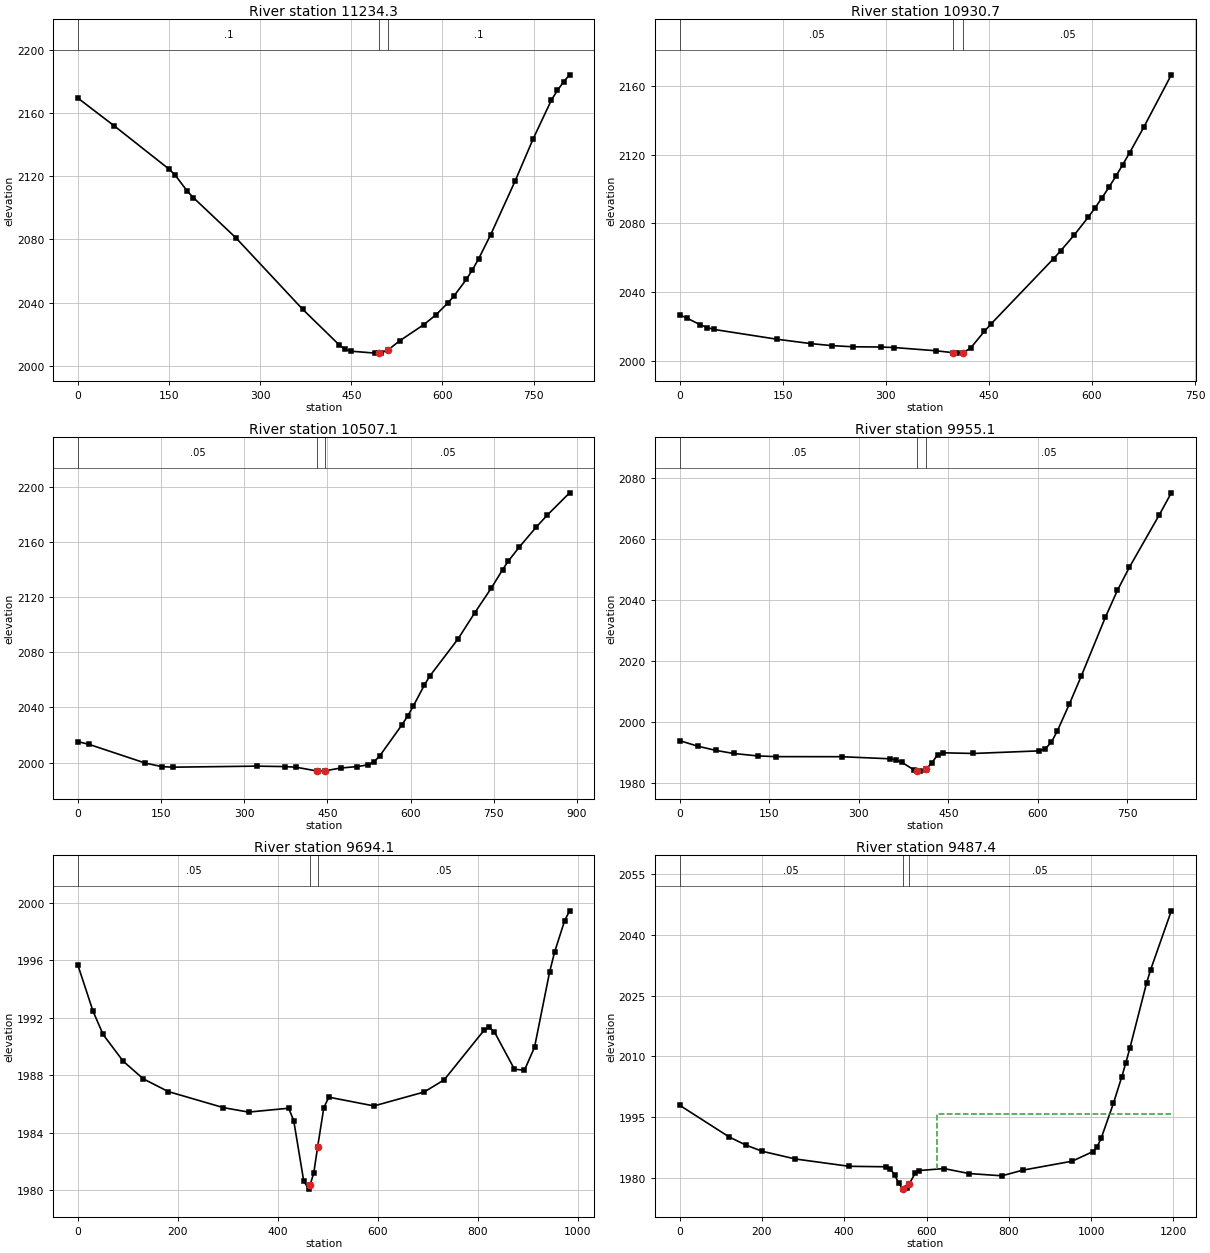
Type RM Length L Ch R = 1 ,11234.3 ,325.6,303.6,281.6
XS GIS Cut Line= 2
     2176888.619      308043.076     2176369.349      307422.251
#Sta/Elev= 30
       0 2169.46      60 2151.82   149.9 2124.54   159.9 2120.82   179.9 2110.59
   189.8 2106.55   259.8 2081.11   369.7 2035.89   429.7 2013.39   439.6  2010.5
   449.6 2009.27   489.6 2008.05   495.8  2008.2   499.6 2008.29   510.8 2010.14
   529.6 2015.84   569.6 2026.15   589.5 2032.35   609.5 2040.01   619.5 2044.46
   639.5 2054.78   649.5 2060.89   659.5 2067.68   679.5 2083.08   719.4 2116.77
   749.4 2143.73   779.4 2168.27   789.4 2174.39   799.4 2179.76   809.4 2184.24
#Mann= 3 , 0 , 0
       0      .1       0   495.8    .045       0   510.8      .1       0
Bank Sta=495.8,510.8
XS Rating Curve= 0 ,0
Exp/Cntr=0.3,0.1

Type RM Length L Ch R = 1 ,10930.7 ,433,423.5,413.8
XS GIS Cut Line= 2
     2177097.655      307418.427      2176383.29      307380.757
#Sta/Elev= 30
       0 2026.69    10.1 2024.95    30.2 2020.94    40.3 2019.34    50.4 2018.24
   141.1 2012.59   191.4 2009.99   221.7 2008.83   251.9 2008.17   292.2 2008.03
   312.3 2007.72   372.8 2005.86   397.8 2004.73     403 2004.47   412.8 2004.82
   423.2 2007.38   443.3 2017.14   453.4 2021.61   544.1 2059.53   554.2 2063.97
   574.3 2073.38   594.4  2083.6   604.5 2089.14   614.6 2094.98   624.7 2101.13
   634.8 2107.58   644.8 2114.32   654.9 2121.32   675.1 2135.91   715.4 2166.58
#Mann= 3 , 0 , 0
       0     .05       0   397.8    .045       0   412.8     .05       0
Bank Sta=397.8,412.8
XS Rating Curve= 0 ,0
Exp/Cntr=0.3,0.1

Type RM Length L Ch R = 1 ,10507.1 ,554.1,552,549.9
XS GIS Cut Line= 2
     2177105.439      306859.031     2176252.244      307101.606
#Sta/Elev= 30
       0  2015.2    20.2 2013.18     121 1999.71   151.2 1997.08   171.4 1996.69
   322.6 1997.45     373 1997.12   393.1 1996.69   431.2 1993.94   433.4 1993.83
   446.2  1994.1   473.7 1996.06     504 1997.14   524.1 1998.44   534.2 2000.59
   544.3 2004.81   584.6 2027.42   594.7 2033.66   604.8 2040.81   624.9 2056.14
     635 2062.86   685.4 2089.43   715.6 2108.37   745.9 2126.55     766  2139.7
   776.1 2145.85   796.3  2156.2   826.5 2170.48   846.7 2179.31     887 2195.44
#Mann= 3 , 0 , 0
       0     .05       0   431.2    .045       0   446.2     .05       0
Bank Sta=431.2,446.2
XS Rating Curve= 0 ,0
Exp/Cntr=0.3,0.1

Type RM Length L Ch R = 1 ,9955.1  ,259.6,261,262.7
XS GIS Cut Line= 2
     2176938.146      306365.516     2176176.962      306680.585
#Sta/Elev= 30
       0 1993.98    30.1 1992.18    60.3  1990.8    90.4 1989.78   130.6 1988.99
   160.7 1988.75   271.3 1988.73   351.6 1988.05   361.7 1987.75   371.7 1986.95
   391.8 1984.51   397.9 1984.21   401.9 1984.01   411.9 1984.46   412.9 1984.67
     422 1986.58     432 1989.31     442    1990   492.3 1989.79   602.8 1990.64
   612.8 1991.33   622.9 1993.51   632.9  1997.2     653 2005.98   673.1  2015.2
   713.3 2034.36   733.4 2043.12   753.5  2050.7   803.7 2067.88   823.8 2075.07
#Mann= 3 , 0 , 0
       0     .05       0   397.9    .045       0   412.9     .05       0
Bank Sta=397.9,412.9
XS Rating Curve= 0 ,0
Exp/Cntr=0.3,0.1

Type RM Length L Ch R = 1 ,9694.1  ,205.5,206.7,207.9
XS GIS Cut Line= 2
     2176931.533      306117.694     2176004.948      306447.496
#Sta/Elev= 30
       0 1995.65    30.1 1992.46    50.2 1990.84    90.3 1988.98   130.5 1987.75
   180.6 1986.86     291 1985.74   341.2 1985.43   421.5  1985.7   431.6 1984.83
   451.6 1980.62   461.7 1980.06   464.3 1980.35   471.7 1981.19   479.3 1982.98
   491.8 1985.74   501.8 1986.47   592.1 1985.86   692.5 1986.83   732.6 1987.68
   812.9 1991.16     823 1991.33     833 1991.02   873.1 1988.42   893.2 1988.35
   913.3 1989.95   943.4 1995.18   953.4 1996.58   973.5 1998.77   983.5 1999.46
#Mann= 3 , 0 , 0
       0     .05       0   464.3    .045       0   479.3     .05       0
Bank Sta=464.3,479.3
XS Rating Curve= 0 ,0
Exp/Cntr=0.3,0.1

Type RM Length L Ch R = 1 ,9487.4  ,356.8,357.6,358.5
XS GIS Cut Line= 2
     2176973.064      305909.838     2175834.904      306274.703
#Sta/Elev= 30
       0 1997.98   120.5 1990.17   160.7 1988.19   200.9 1986.65   281.2 1984.76
   411.8 1982.96   502.2 1982.84   512.2  1982.3   522.3 1980.88   532.3 1978.84
   542.3 1977.34   552.4 1977.56   557.3 1978.49   572.5 1981.26   582.5 1981.92
   642.8  1982.4   703.1 1981.18   783.4 1980.62   833.6    1982   954.2 1984.22
  1004.4 1986.57  1014.4 1987.67  1024.5 1989.81  1054.6 1998.52  1074.7 2004.97
  1084.7 2008.47  1094.8 2012.19    1135 2028.08    1145 2031.38  1195.2 2045.85
#Mann= 3 , 0 , 0
       0     .05       0   542.3    .045       0   557.3     .05       0
#XS Ineff= 2 , 0
                          624.61         1995.77
Permanent Ineff=
       F       F
Bank Sta=542.3,557.3
XS Rating Curve= 0 ,0
Exp/Cntr=0.3,0.1

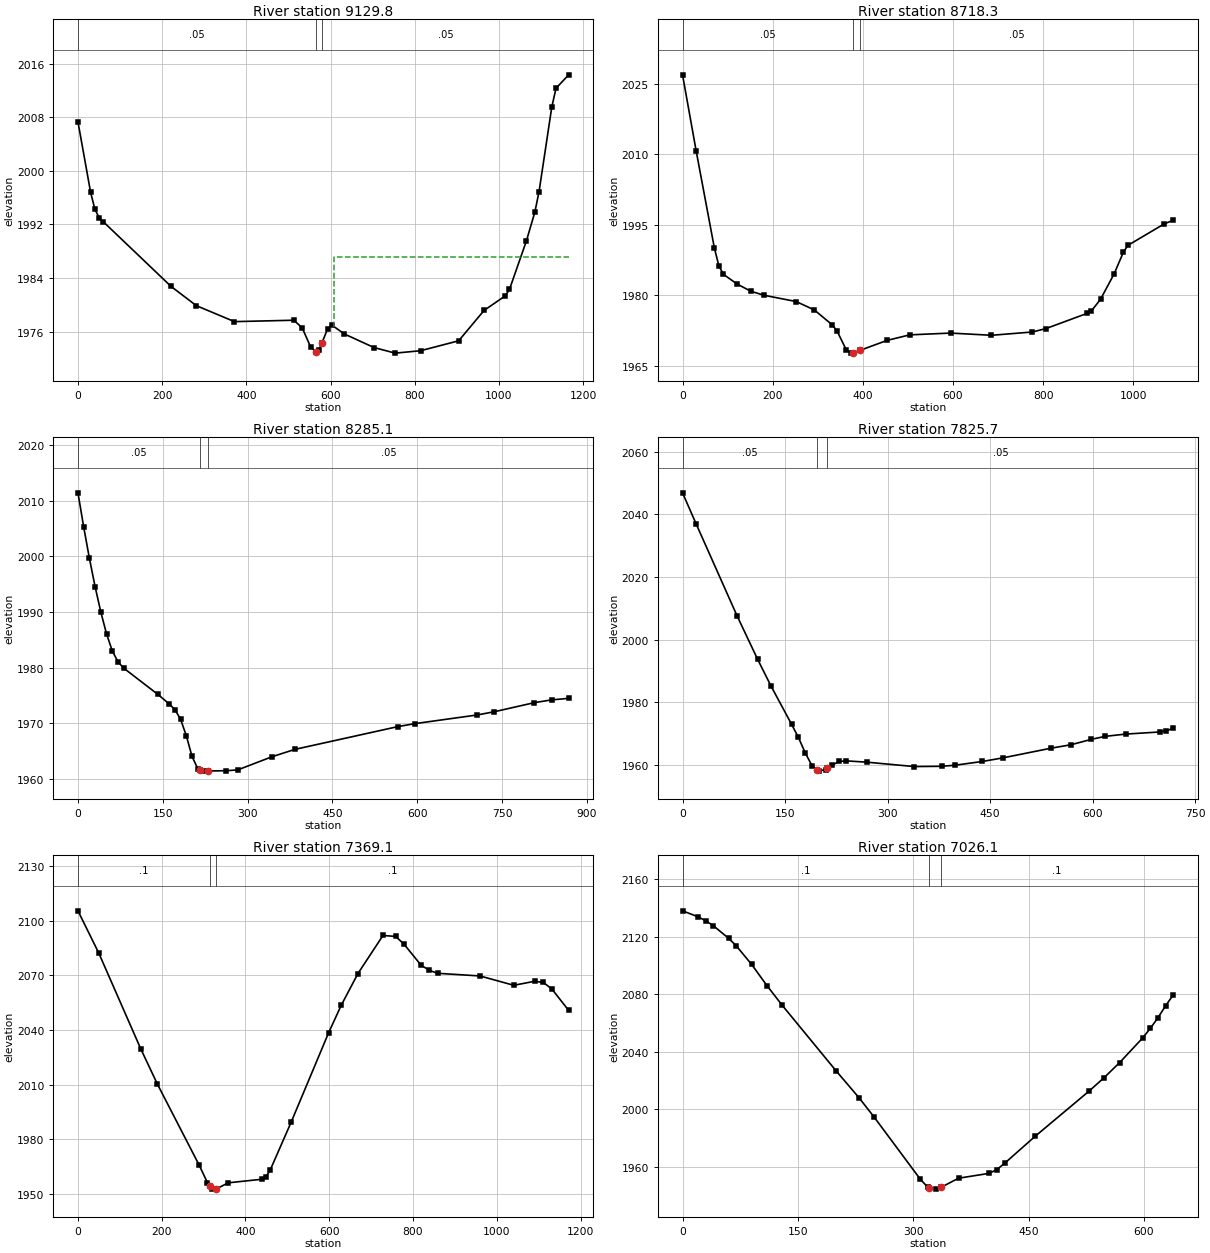
Type RM Length L Ch R = 1 ,9129.8  ,412.2,411.5,410.8
XS GIS Cut Line= 2
     2176853.258      305599.431     2175731.435      305915.284
#Sta/Elev= 30
       0  2007.3    30.1 1996.76    40.2 1994.26    50.2    1993    60.3 1992.38
     221 1982.74   281.3 1979.86   371.7 1977.48   512.4 1977.69   532.5 1976.57
   552.6 1973.69   564.6 1973.01   572.7 1973.31   579.6 1974.33   592.8 1976.38
   602.8 1976.97     633 1975.63   703.3 1973.61   753.5 1972.78   813.8 1973.14
   904.2 1974.62   964.5 1979.15  1014.7 1981.32  1024.8 1982.28    1065 1989.51
  1085.1 1993.82  1095.1 1996.88  1125.2 2009.44  1135.3  2012.3  1165.4 2014.31
#Mann= 3 , 0 , 0
       0     .05       0   564.6    .045       0   579.6     .05       0
#XS Ineff= 2 , 0
                           608.2         1987.13
Permanent Ineff=
       F       F
Bank Sta=564.6,579.6
XS Rating Curve= 0 ,0
Exp/Cntr=0.3,0.1

Type RM Length L Ch R = 1 ,8718.3  ,433.9,433.2,432.5
XS GIS Cut Line= 2
     2176706.223      305240.012     2175666.086      305561.311
#Sta/Elev= 30
       0 2026.85    30.2 2010.71    70.6 1990.08    80.6 1986.27    90.7 1984.47
     121 1982.41   151.2 1980.89   181.4 1980.01     252 1978.69   292.3 1976.91
   332.6  1973.7   342.7 1972.45   362.9  1968.5     373 1967.73   378.2 1967.81
   393.2  1968.3   453.6 1970.43     504 1971.61   594.7 1971.99   685.4 1971.52
   776.2 1972.22   806.4 1972.95   897.1 1976.16   907.2  1976.7   927.4 1979.18
   957.6 1984.59   977.8 1989.12   987.8 1990.61  1068.5 1995.18  1088.6 1995.97
#Mann= 3 , 0 , 0
       0     .05       0   378.2    .045       0   393.2     .05       0
Bank Sta=378.2,393.2
XS Rating Curve= 0 ,0
Exp/Cntr=0.3,0.1

Type RM Length L Ch R = 1 ,8285.1  ,461,459.4,457.7
XS GIS Cut Line= 2
     2176472.056       304858.81     2175649.749      305136.543
#Sta/Elev= 30
       0 2011.41    10.1 2005.31    20.2 1999.68    30.3 1994.57    40.4 1990.02
    50.5 1986.11    60.6 1983.06    70.6  1981.1    80.7 1979.95   141.3 1975.22
   161.5  1973.5   171.6 1972.48   181.7 1970.71   191.8 1967.74   201.8 1964.08
   211.9 1961.89   215.7 1961.72     222 1961.44   230.7 1961.47   262.4 1961.51
   282.6 1961.66   343.1 1964.02   383.5 1965.34   565.2 1969.42   595.4 1969.96
   706.5 1971.53   736.7 1972.11   807.4 1973.74   837.7 1974.23   867.9 1974.51
#Mann= 3 , 0 , 0
       0     .05       0   215.7    .045       0   230.7     .05       0
Bank Sta=215.7,230.7
XS Rating Curve= 0 ,0
Exp/Cntr=0.3,0.1

Type RM Length L Ch R = 1 ,7825.7  ,434.1,456.5,479
XS GIS Cut Line= 2
     2176325.021      304412.259      2175660.64      304684.546
#Sta/Elev= 30
       0 2046.88    19.9 2036.96    79.8 2007.57   109.7 1993.76   129.6 1985.08
   159.6  1972.9   169.5 1968.74   179.5 1963.82   189.5 1959.64     197 1958.36
   199.4 1957.95   209.4 1958.47     212 1958.86   219.4 1959.96   229.4 1961.04
   239.3 1961.23   269.2 1960.82   339.1 1959.41     379 1959.49   398.9 1959.84
   438.8 1961.04   468.7 1962.18   538.5 1965.25   568.4 1966.38   598.3 1968.11
   618.3 1969.06   648.2 1969.78   698.1 1970.46     708 1970.89     718 1971.59
#Mann= 3 , 0 , 0
       0     .05       0     197    .045       0     212     .05       0
Bank Sta=197,212
XS Rating Curve= 0 ,0
Exp/Cntr=0.3,0.1

Type RM Length L Ch R = 1 ,7369.1  ,339,343.1,347.2
XS GIS Cut Line= 3
     2176341.358      304199.875     2175687.869      303878.576
     2175421.028       304232.55
#Sta/Elev= 30
       0 2105.54    49.9 2082.22   149.6 2029.82   189.5 2010.33   289.3 1965.73
   309.2 1956.02   314.7 1954.23   319.2 1952.76   329.2  1952.5   329.7 1952.57
   359.1 1955.98   438.9 1957.93   448.9 1959.26   458.9 1962.95   508.8 1989.22
   598.5 2038.51   628.4 2053.51   668.4 2071.04   728.2 2091.98   758.4 2091.47
   778.6 2087.17   818.9 2075.72     839 2072.78   859.2 2071.18   959.9 2069.72
  1040.5 2064.59  1090.9 2066.82    1111 2066.14  1131.2 2062.62  1171.5 2050.79
#Mann= 3 , 0 , 0
       0      .1       0   314.7    .045       0   329.7      .1       0
Bank Sta=314.7,329.7
XS Rating Curve= 0 ,0
Exp/Cntr=0.3,0.1

Type RM Length L Ch R = 1 ,7026.1  ,471.5,466.5,461.5
XS GIS Cut Line= 2
      2176508.76      303962.071     2175987.363      303594.026
#Sta/Elev= 30
       0 2137.86    19.9 2133.77    29.9 2131.04    39.9  2127.6    59.8 2118.83
    69.8  2113.6    89.8 2100.68   109.7 2085.97   129.6 2072.26   199.4  2026.9
   229.4 2008.09   249.3  1994.5   309.1 1951.51   319.1 1945.78   320.9 1945.55
   329.1 1944.52   335.9  1945.7     359  1952.1   398.9 1955.48   408.8  1958.1
   418.8 1962.42   458.7 1981.26   528.5  2012.5   548.5 2022.05   568.4 2032.39
   598.3 2049.44   608.3 2056.12   618.3 2063.54   628.2 2071.82   638.2 2079.46
#Mann= 3 , 0 , 0
       0      .1       0   320.9    .045       0   335.9      .1       0
Bank Sta=320.9,335.9
XS Rating Curve= 0 ,0
Exp/Cntr=0.3,0.1