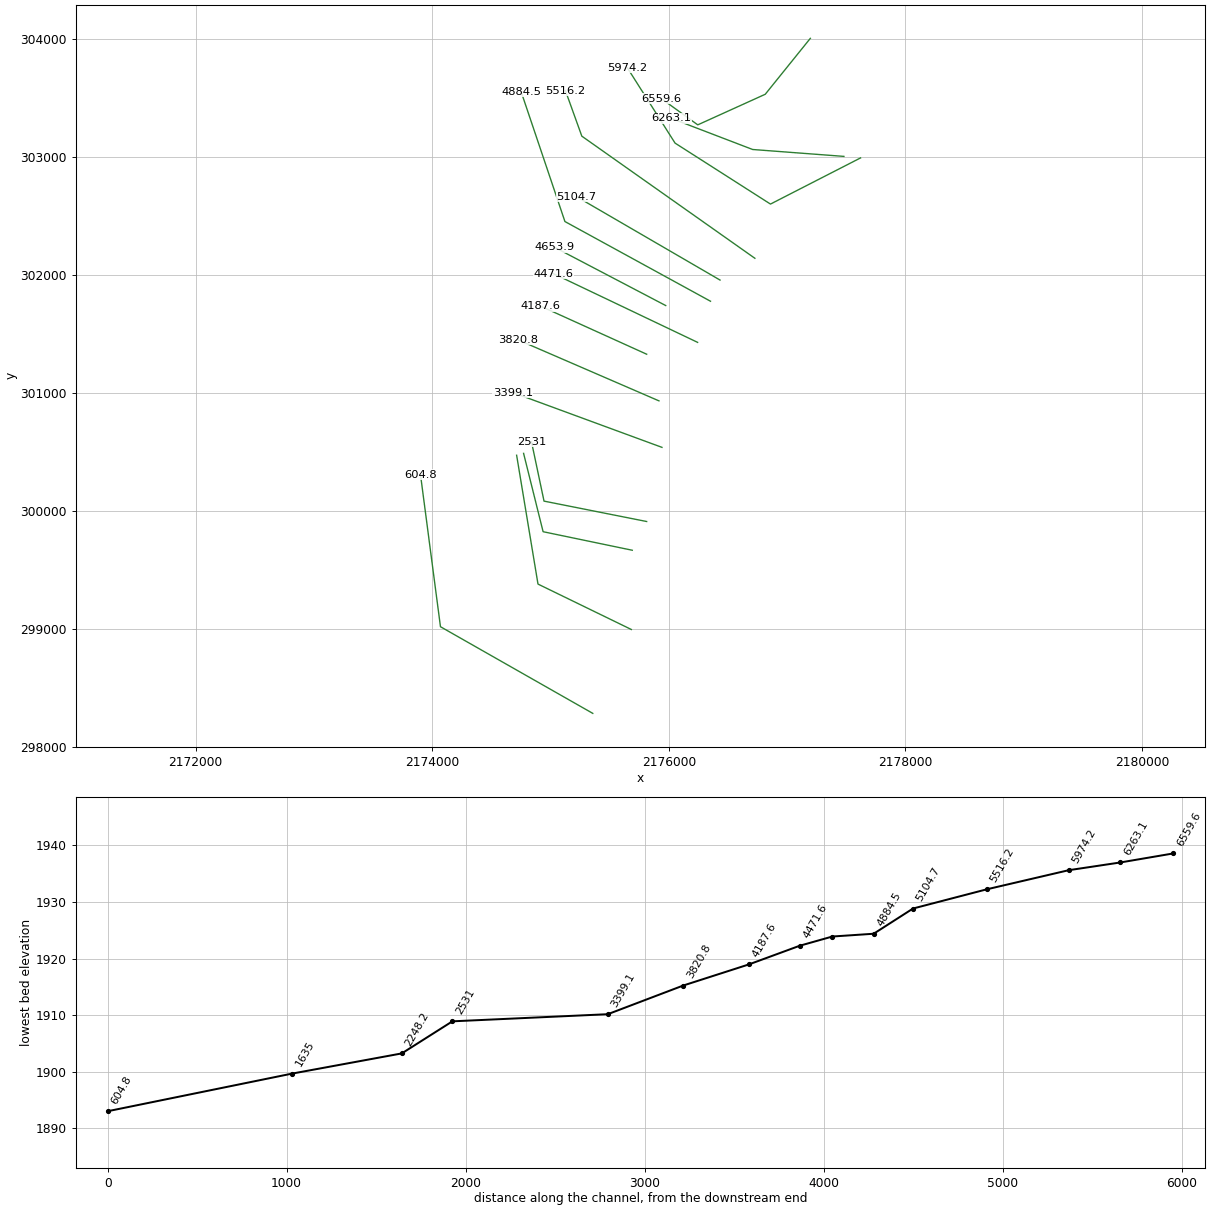
HEC-RAS study JerichDr.prj: JerichDr

--- JerichDr.g01 (geometry) --- (continued)

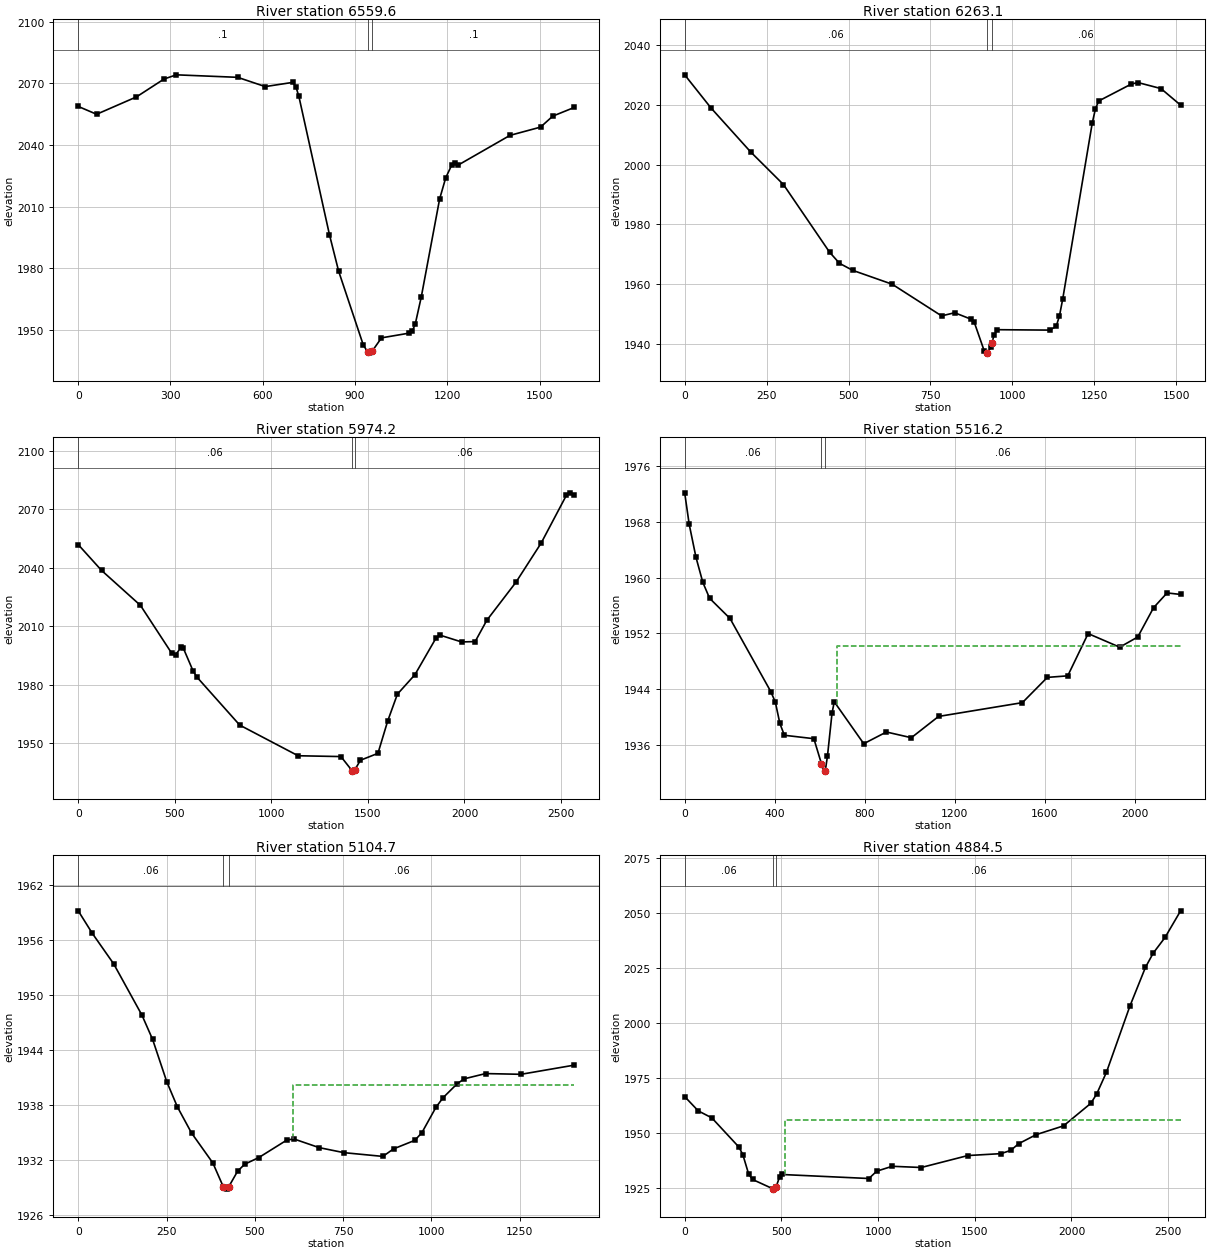
Type RM Length L Ch R = 1 ,6559.6  ,317.7,296.5,275.3
XS GIS Cut Line= 4
      2177196.34      304003.829     2176815.138      303530.049
     2176244.531      303270.828     2175938.373      303491.929
#Sta/Elev= 30
       0 2058.76    59.8 2054.94   189.4  2063.4   279.1 2072.11     319 2074.15
   518.4 2072.93   608.1 2068.42   697.6 2070.47   707.6 2068.43   717.5 2063.62
     817 1996.21   846.8 1978.48   926.4 1942.78   941.5 1938.98   946.3  1938.6
   956.5 1939.71   986.1 1946.04  1075.7 1948.33  1085.6 1949.21  1095.6 1952.58
  1115.4 1965.94  1175.1 2013.69    1195 2024.03  1214.9 2030.35  1224.9  2031.2
  1234.8 2030.14  1403.8 2044.66  1503.2 2048.68  1542.9 2054.03  1612.5 2058.24
#Mann= 3 , 0 , 0
       0      .1       0   941.5    .045       0   956.5      .1       0
Bank Sta=941.5,956.5
XS Rating Curve= 0 ,0
Exp/Cntr=0.3,0.1

Type RM Length L Ch R = 1 ,6263.1  ,294.1,288.9,283.7
XS GIS Cut Line= 3
     2177480.441      303003.676     2176708.772      303062.073
     2176018.442      303326.943
#Sta/Elev= 30
       0 2029.97    80.4 2018.89     201 2004.25   301.5  1993.3   442.2 1970.71
   472.4    1967   512.6 1964.66   633.2 1960.02   783.9 1949.44   823.8 1950.49
   873.8 1948.34   883.8 1947.25   913.8 1937.82   922.5 1937.11   923.8    1937
   933.8  1938.9   937.5 1940.39   943.7 1942.89   953.7 1944.83  1113.6 1944.69
  1133.6 1945.92  1143.6 1949.44  1153.6 1955.11  1243.5 2013.77  1253.5 2018.67
  1263.5 2021.24  1363.4 2026.92  1383.4 2027.38  1453.3 2025.38  1513.3 2019.84
#Mann= 3 , 0 , 0
       0     .06       0   922.5    .045       0   937.5     .06       0
Bank Sta=922.5,937.5
XS Rating Curve= 0 ,0
Exp/Cntr=0.3,0.1

Type RM Length L Ch R = 1 ,5974.2  ,463.9,458,449.6
XS GIS Cut Line= 4
     2177621.107      302990.921      2176859.24      302599.665
     2176052.734      303116.173     2175649.749      303753.324
#Sta/Elev= 30
       0 2051.87   120.9 2038.61   322.4 2020.66   483.6  1996.2   503.8 1995.32
     534 1999.26   544.1 1998.76   594.5 1987.12   614.6 1983.89   836.3 1959.25
  1138.7 1943.52  1360.5  1943.1  1417.3 1935.95    1421 1935.63  1432.3 1936.29
  1461.3 1941.21  1552.1 1944.76  1602.5 1961.33  1652.9 1975.14  1743.6 1985.11
  1854.4 2004.18  1874.5 2005.37  1985.1 2001.92  2055.4  2002.1  2115.7 2013.01
  2266.5 2032.52  2397.2 2052.64  2527.9 2077.16    2548 2078.43  2568.1 2077.46
#Mann= 3 , 0 , 0
       0     .06       0  1417.3    .045       0  1432.3     .06       0
Bank Sta=1417.3,1432.3
XS Rating Curve= 0 ,0
Exp/Cntr=0.3,0.1

Type RM Length L Ch R = 1 ,5516.2  ,403.5,411.5,422.1
XS GIS Cut Line= 3
      2176727.37      302140.447     2175264.385      303175.146
     2175125.478      303561.734
#Sta/Elev= 30
       0 1972.15    20.1 1967.63    50.3 1962.89    80.5 1959.32   110.7 1957.03
   201.3 1954.14   382.5 1943.65   402.7 1942.14   422.8 1939.08   442.9 1937.39
   573.8  1936.9   607.2 1933.34   622.2  1932.3   624.2 1932.25   634.2 1934.41
   654.4 1940.56   664.4 1942.19   795.3 1936.18     896 1937.86  1006.7 1937.04
  1127.5 1940.09    1500 1942.07  1610.7 1945.69  1701.3 1945.91  1791.9 1951.97
  1932.2 1950.02  2012.3 1951.48  2082.5 1955.68  2142.6  1957.8  2202.7 1957.58
#Mann= 3 , 0 , 0
       0     .06       0   607.2    .045       0   622.2     .06       0
#XS Ineff= 2 , 0
                          674.57         1950.13
Permanent Ineff=
       F       F
Bank Sta=607.2,622.2
XS Rating Curve= 0 ,0
Exp/Cntr=0.3,0.1

Type RM Length L Ch R = 1 ,5104.7  ,220.2,220.2,220.2
XS GIS Cut Line= 2
     2176432.905      301955.915     2175219.707      302662.632
#Sta/Elev= 30
       0 1959.23    40.1 1956.76   100.3 1953.45   180.5 1947.84   210.6  1945.2
   250.7 1940.58   280.8 1937.83   320.9 1934.98   381.1 1931.72   410.7 1929.12
   421.2 1928.86   425.7 1929.09   451.3 1930.82   471.4 1931.58   511.5 1932.31
   591.7 1934.24   611.8 1934.32     682 1933.39   752.2 1932.84   862.5 1932.43
   892.6 1933.25   952.7 1934.18   972.8 1935.01  1012.9  1937.8    1033 1938.84
  1073.1 1940.37  1093.1  1940.9  1153.3 1941.47  1253.6 1941.39    1404 1942.39
#Mann= 3 , 0 , 0
       0     .06       0   410.7    .045       0   425.7     .06       0
#XS Ineff= 2 , 0
                           608.2         1940.27
Permanent Ineff=
       F       F
Bank Sta=410.7,425.7
XS Rating Curve= 0 ,0
Exp/Cntr=0.3,0.1

Type RM Length L Ch R = 1 ,4884.5  ,229.8,230.6,231.6
XS GIS Cut Line= 3
      2176352.25       301776.52     2175121.512      302451.792
     2174751.201      303551.832
#Sta/Elev= 30
       0 1966.51    70.2    1960   140.4 1956.82   280.8  1943.5   300.8 1940.06
   330.9 1931.22     351 1928.79   457.7 1924.49   461.2  1924.4   472.7 1925.46
   491.3 1930.07   501.4 1931.06   952.6 1929.23   992.7 1932.55  1072.9 1934.79
  1223.3 1934.24  1464.4 1939.68    1636 1940.55  1686.4 1942.05  1726.8 1945.06
  1817.6 1949.19  1958.9 1953.18  2100.2 1963.44  2130.5 1967.69    2181 1977.58
  2302.1 2007.64  2382.8 2025.33  2423.2 2031.83  2483.8 2038.89  2564.5 2051.02
#Mann= 3 , 0 , 0
       0     .06       0   457.7    .045       0   472.7     .06       0
#XS Ineff= 2 , 0
                          516.86         1955.66
Permanent Ineff=
       F       F
Bank Sta=457.7,472.7
XS Rating Curve= 0 ,0
Exp/Cntr=0.3,0.1

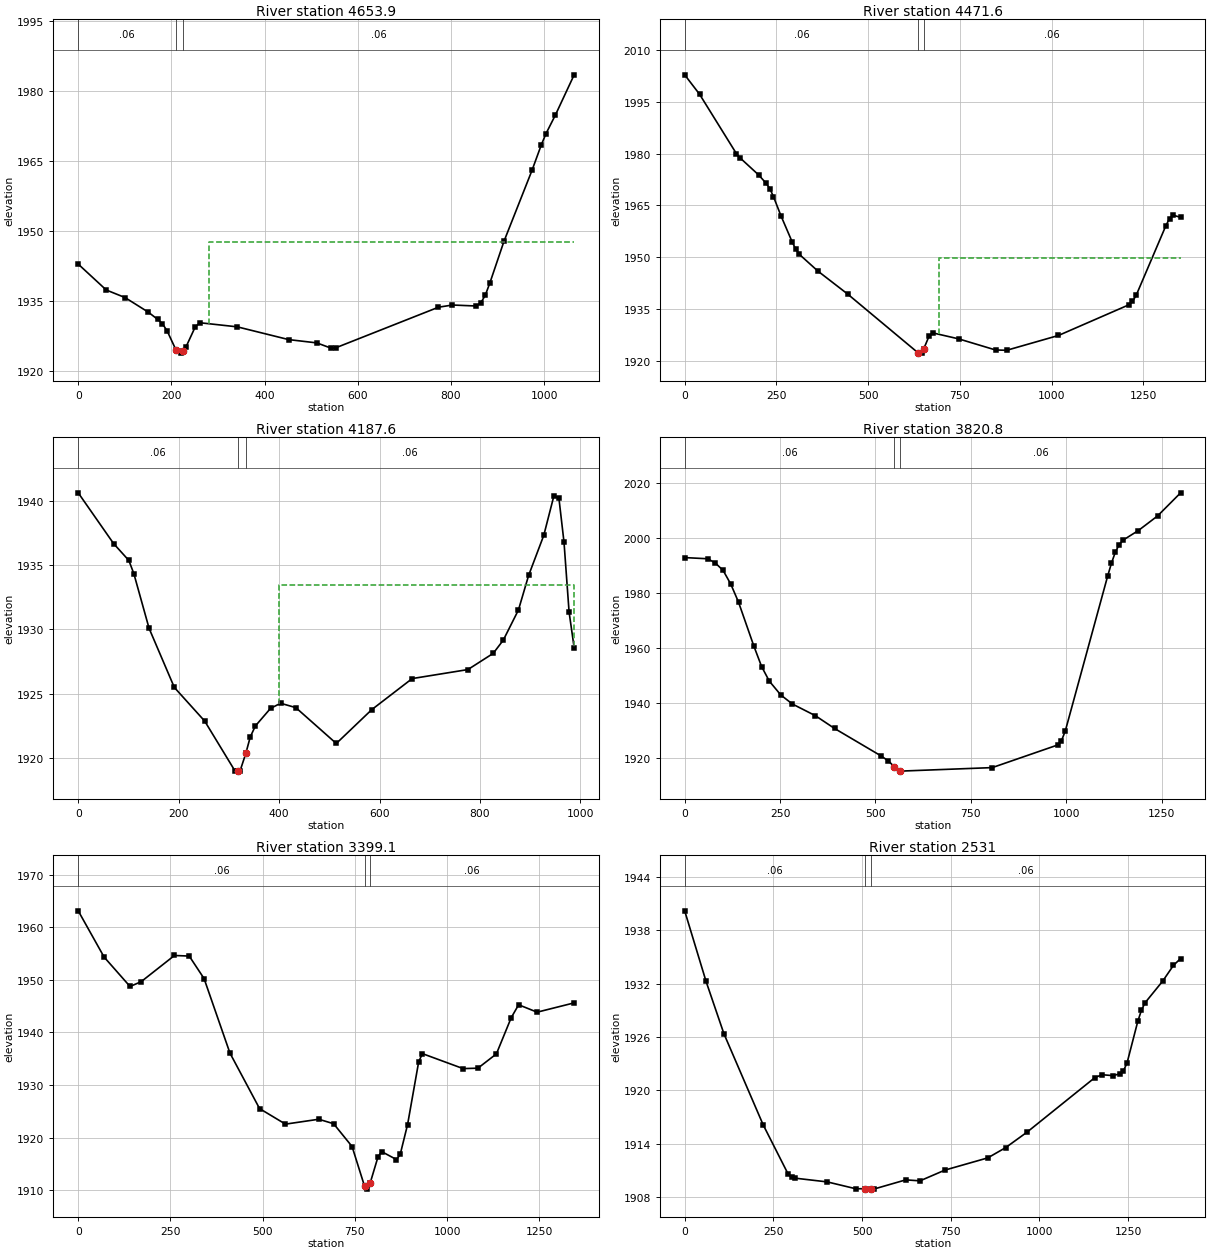
Type RM Length L Ch R = 1 ,4653.9  ,181.7,182.3,182.7
XS GIS Cut Line= 2
     2175973.539      301739.974     2175031.249      302234.676
#Sta/Elev= 30
       0 1942.95    60.2 1937.41   100.4  1935.8   150.6 1932.66   170.7 1931.11
   180.7 1930.21   190.8 1928.67   210.3 1924.48   220.9 1923.91   225.3 1924.46
   230.9 1925.15     251 1929.49     261 1930.41   341.4 1929.53   451.8  1926.8
     512  1926.1   542.2 1924.99   552.2 1925.03   773.1 1933.73   803.2  1934.2
   853.4 1933.99   863.4 1934.57   873.5 1936.27   883.5 1938.94   913.6  1947.8
   973.9 1963.01     994  1968.5    1004 1970.88  1024.1 1974.84  1064.3 1983.43
#Mann= 3 , 0 , 0
       0     .06       0   210.3    .045       0   225.3     .06       0
#XS Ineff= 2 , 0
                          280.04         1947.66
Permanent Ineff=
       F       F
Bank Sta=210.3,225.3
XS Rating Curve= 0 ,0
Exp/Cntr=0.3,0.1

Type RM Length L Ch R = 1 ,4471.6  ,283.5,284,284.5
XS GIS Cut Line= 2
     2176243.335      301427.993     2175023.488      302010.687
#Sta/Elev= 30
       0 2002.76    40.4 1997.17   141.2 1979.94   151.3 1978.71   201.8 1973.79
     222  1971.4     232 1969.87   242.1 1967.52   262.3 1962.04   292.6 1954.54
   302.7 1952.34   312.8 1950.82   363.2    1946   443.9 1939.39   636.7 1922.32
   645.7 1922.28   651.7 1923.52   665.8  1927.1   675.9 1928.14   746.6 1926.41
   847.4 1923.19   877.7  1923.1    1019 1927.39  1210.6 1936.24  1220.7 1937.21
  1230.8 1939.01  1311.5 1959.08  1321.6  1961.2  1331.7 1962.16  1351.9 1961.55
#Mann= 3 , 0 , 0
       0     .06       0   636.7    .045       0   651.7     .06       0
#XS Ineff= 2 , 0
                          694.26         1949.78
Permanent Ineff=
       F       F
Bank Sta=636.7,651.7
XS Rating Curve= 0 ,0
Exp/Cntr=0.3,0.1

Type RM Length L Ch R = 1 ,4187.6  ,364.8,366.8,367.6
XS GIS Cut Line= 2
     2175812.564      301327.722     2174913.463      301736.048
#Sta/Elev= 30
       0 1940.63    70.5 1936.68   100.8 1935.37   110.8 1934.34   141.1 1930.09
   191.4 1925.49   251.9 1922.87   312.4 1918.98   318.7    1919   322.4 1919.01
   333.7 1920.36   342.6 1921.64   352.7 1922.49   382.9 1923.86     403 1924.26
   433.3 1923.92   513.9 1921.13   584.4 1923.76     665 1926.18   775.9 1926.88
   826.3 1928.14   846.4 1929.17   876.6 1931.52   896.8  1934.2     927 1937.32
   947.2  1940.4   957.2  1940.2   967.3 1936.79   977.4 1931.36   987.5 1928.58
#Mann= 3 , 0 , 0
       0     .06       0   318.7    .045       0   333.7     .06       0
#XS Ineff= 2 , 0
                          399.27         1933.48
Permanent Ineff=
       F       F
Bank Sta=318.7,333.7
XS Rating Curve= 0 ,0
Exp/Cntr=0.3,0.1

Type RM Length L Ch R = 1 ,3820.8  ,419.9,421.7,433.5
XS GIS Cut Line= 2
      2175916.59       300932.43     2174723.973      301449.776
#Sta/Elev= 30
       0 1992.94    60.5 1992.51    80.6 1990.94   100.8 1988.26   120.9 1983.27
   141.1 1976.74   181.4 1960.72   201.6 1953.31   221.7 1948.02   251.9 1942.96
   282.2 1939.68   342.6 1935.42     393 1930.76     514 1920.85   534.1 1918.94
   549.6 1916.84   564.3 1915.25   564.6 1915.25   806.2 1916.53   977.5 1924.75
   987.6 1926.29   997.7 1929.86  1108.5 1986.09  1118.6 1990.86  1128.7 1994.86
  1138.8 1997.62  1148.8 1999.26  1189.1 2002.77  1239.5 2008.08    1300  2016.5
#Mann= 3 , 0 , 0
       0     .06       0   549.6    .045       0   564.6     .06       0
Bank Sta=549.6,564.6
XS Rating Curve= 0 ,0
Exp/Cntr=0.3,0.1

Type RM Length L Ch R = 1 ,3399.1  ,867.8,868.1,859.8
XS GIS Cut Line= 2
     2175942.129      300538.555     2174680.407      301003.225
#Sta/Elev= 30
       0 1963.15    70.2 1954.35   140.5 1948.75   170.6 1949.66   260.9 1954.65
     301 1954.54   341.2 1950.26   411.4 1936.07   491.7 1925.51   561.9 1922.55
   652.2 1923.48   692.4 1922.63   742.5 1918.29   776.3 1910.74   782.7 1910.18
   791.3 1911.28   812.8 1916.32   822.8 1917.32   862.9 1915.81     873 1916.79
     893 1922.48   923.1 1934.42   933.2 1935.97  1043.5 1933.12  1083.7  1933.2
  1133.8 1935.92    1174 1942.82  1194.1 1945.27  1244.2 1943.86  1344.6 1945.63
#Mann= 3 , 0 , 0
       0     .06       0   776.3    .045       0   791.3     .06       0
Bank Sta=776.3,791.3
XS Rating Curve= 0 ,0
Exp/Cntr=0.3,0.1

Type RM Length L Ch R = 1 ,2531    ,278.9,282.8,285
XS GIS Cut Line= 3
     2175812.564      299910.361     2174944.873      300083.115
     2174838.865      300585.669
#Sta/Elev= 30
       0 1940.18    60.3 1932.25   110.6 1926.38   221.2 1916.15   291.6 1910.62
   301.6 1910.23   311.7 1910.15   402.2 1909.73   482.6 1908.96   509.7 1908.97
   524.7 1908.93   532.8 1908.92   623.3 1909.96   663.5 1909.85   733.9 1911.06
   854.6 1912.43   904.9 1913.58   965.3 1915.32  1156.6 1921.45  1176.8 1921.77
    1207 1921.67  1227.1 1921.87  1237.2 1922.22  1247.3  1923.1  1277.5 1927.76
  1287.6 1928.99  1297.6 1929.83    1348  1932.3  1378.2 1934.06  1398.3 1934.82
#Mann= 3 , 0 , 0
       0     .06       0   509.7    .045       0   524.7     .06       0
Bank Sta=509.7,524.7
XS Rating Curve= 0 ,0
Exp/Cntr=0.3,0.1

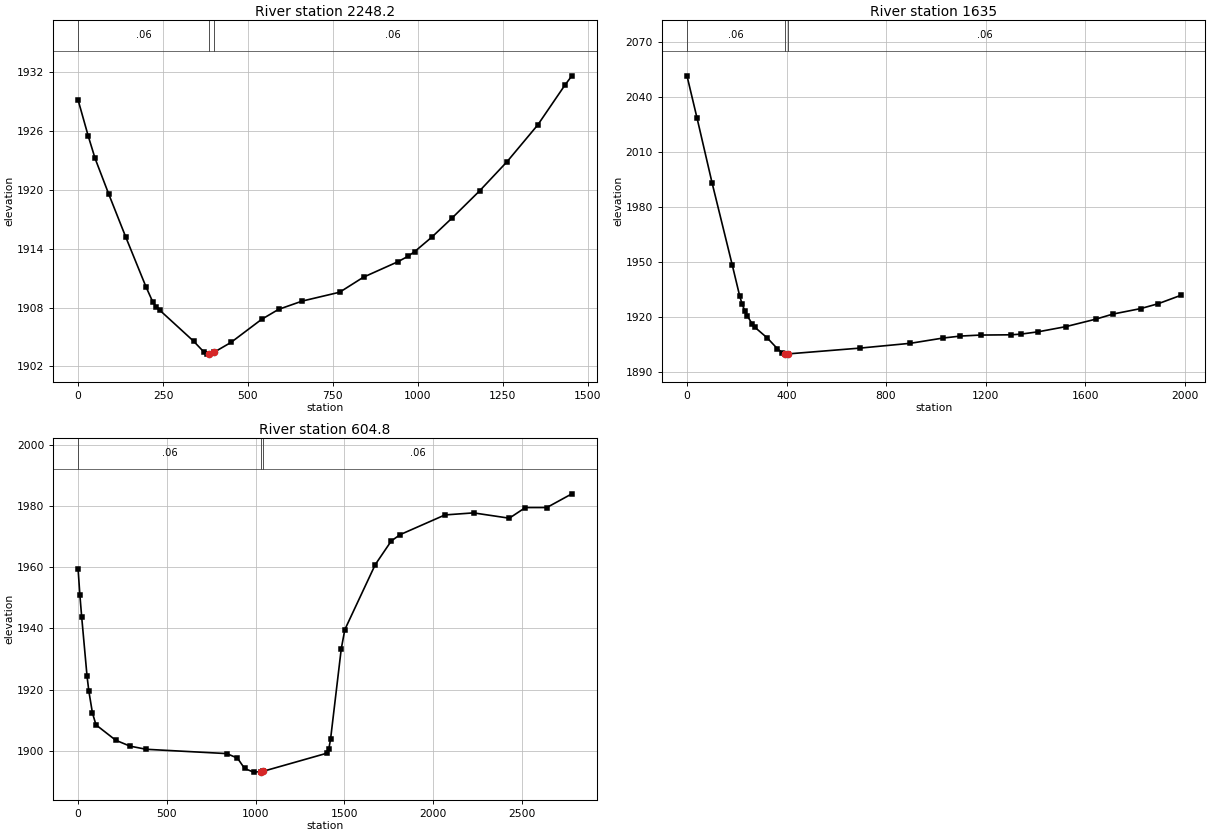
Type RM Length L Ch R = 1 ,2248.2  ,620.2,613.2,606.2
XS GIS Cut Line= 3
     2175690.852      299666.937      2174937.02      299823.985
      2174772.12      300487.514
#Sta/Elev= 30
       0 1929.15      30 1925.46      50  1923.2      90 1919.58     140 1915.21
     200  1910.1     220 1908.56     230 1908.08     240 1907.74     340 1904.57
     370 1903.48     380 1903.25   384.7 1903.26   399.7 1903.43     450 1904.44
     540 1906.79     590 1907.81     660 1908.66     770 1909.56   840.4  1911.1
     941 1912.66   971.1 1913.22   991.2 1913.71  1041.5 1915.18  1101.8 1917.15
  1182.3  1919.9  1262.7 1922.86  1353.2 1926.61  1433.6 1930.69  1453.7 1931.62
#Mann= 3 , 0 , 0
       0     .06       0   384.7    .045       0   399.7     .06       0
Bank Sta=384.7,399.7
XS Rating Curve= 0 ,0
Exp/Cntr=0.3,0.1

Type RM Length L Ch R = 1 ,1635    ,1028.2,1030.2,1029.8
XS GIS Cut Line= 3
     2175682.999      298995.555     2174893.832      299380.324
     2174713.226      300471.809
#Sta/Elev= 30
       0 2051.48    40.4 2028.47   100.9 1993.08   181.6  1948.5   211.9 1931.37
     222 1926.78   232.1 1923.44   242.2 1920.64   262.4 1916.06   272.5 1914.37
   322.9 1908.48   363.3 1902.65   383.5 1900.36   392.9 1899.73   393.6 1899.68
   407.9 1899.82   696.3 1902.98   898.1 1905.59  1028.8 1908.45  1099.2 1909.53
  1179.7 1910.08  1300.4 1910.22  1340.6 1910.57    1411 1911.85  1521.6 1914.65
  1642.3 1918.73  1712.7 1921.56  1823.4 1924.52  1893.8 1927.18  1984.3 1931.73
#Mann= 3 , 0 , 0
       0     .06       0   392.9    .045       0   407.9     .06       0
Bank Sta=392.9,407.9
XS Rating Curve= 0 ,0
Exp/Cntr=0.3,0.1

Type RM Length L Ch R = 1 ,604.8   ,613.4,604.8,598.7
XS GIS Cut Line= 3
     2175357.124      298284.912     2174069.328      299019.112
     2173900.502      300306.908
#Sta/Elev= 30
       0 1959.39    10.1 1950.86    20.2 1943.74    50.4 1924.37    60.5 1919.53
    80.7 1912.38   100.8 1908.48   211.8 1903.46   292.4 1901.53   383.2  1900.5
     837 1899.09   897.5 1897.62   937.8 1894.22   988.3 1893.03  1028.9 1893.17
  1043.9 1893.33  1401.7 1899.22  1411.8  1900.5  1421.9 1903.75  1482.4  1933.4
  1502.5 1939.64  1673.7 1960.87  1764.3 1968.63  1814.6 1970.69  2066.4 1977.12
  2227.4 1977.79  2428.8 1976.05  2519.4 1979.53  2640.2 1979.54  2781.2 1984.02
#Mann= 3 , 0 , 0
       0     .06       0  1028.9    .045       0  1043.9     .06       0
Bank Sta=1028.9,1043.9
XS Rating Curve= 0 ,0
Exp/Cntr=0.3,0.1

Chan Stop Cuts=-1
Use User Specified Reach Order=0